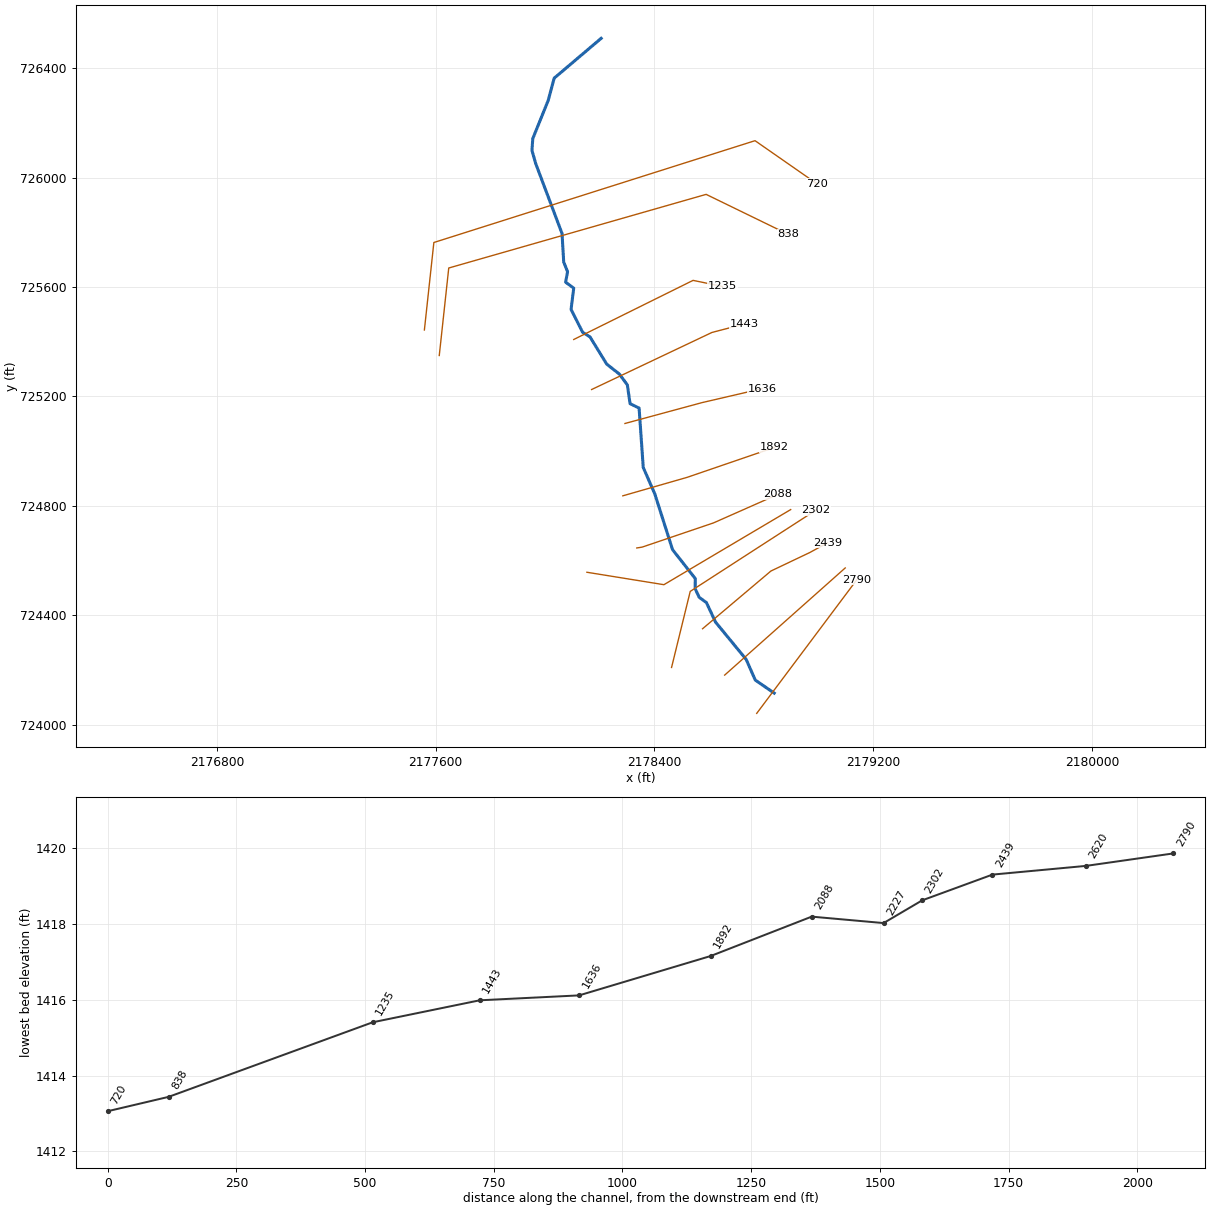
--- BRUSHYFKT1.prj (project) ---

Proj Title=BRUSHYFKT1
Current Plan=p01
Default Exp/Contr=0,0
English Units
Geom File=g01
Flow File=f01
Plan File=p01
BEGIN DESCRIPTION:
---------- MODELED AS PART OF WVEMD CTP PROGRAM, 2023----------
Stream Name: Brushy Fork Tributary 1
Flood Zone:  AFH
Upshur County, WV
HEC-RAS Version: RAS 6.3
Vertical Datum: NAVD88
Projection: NAD 1983 StatePlane West Virginia S FIPS 4702 (US Feet)
Terrain: 1-meter LIDAR (FEMA Region III 3DEP collected 2016-2018)
Land Use: 2019 NLCD
Hydrologic Method:
WV SIR2010-5033 regression equations
Additional Model Notes:
None
END DESCRIPTION:
DSS Export Rating Curves= 0
DSS Export Rating Curve Sorted= 0
DSS Export Volume Flow Curves= 0
DXF OffsetX= 0
DXF OffsetY= 0
DXF ScaleX= 0
DXF ScaleY= 0

--- BRUSHYFKT1.p01 (plan) ---

Plan Title=Floodplain
Program Version=6.30
Short Identifier=Floodplain
Geom File=g01
Flow File=f01
Subcritical Flow
K Sum by GR= 0
Std Step Tol= 0.01
Critical Tol= 0.01
Num of Std Step Trials= 20
Max Error Tol= 0.3
Flow Tol Ratio= 0.001
Split Flow NTrial= 30
Split Flow Tol= 0.02
Split Flow Ratio= 0.02
Log Output Level= 0
Friction Slope Method= 1
Unsteady Friction Slope Method= 2
Unsteady Bridges Friction Slope Method= 1
Parabolic Critical Depth
Global Vel Dist= 0 , 0 , 0
Global Log Level= 0
CheckData=False
Encroach Param=-1 ,0,0, 0
Mapping Interval=1HOUR
Computation Time Step Use Courant=        0
Computation Time Step Use Time Series=    0
Computation Time Step Count To Double=0
Computation Time Step Max Doubling=0
Computation Time Step Max Halving=0
Computation Time Step Residence Courant=0
Run HTab= 0
Run UNet= 0
Run Sediment= 0
Run PostProcess= 0
Run WQNet= 0
Run RASMapper=-1
UNET Theta= 0
UNET Theta Warmup= 0
UNET ZTol= 0
UNET ZSATol= 0
UNET MxIter= 0
UNET Max Iter WO Improvement= 0
UNET MaxInSteps= 0
UNET DtIC= 0
UNET DtMin= 0
UNET MaxCRTS= 0
UNET WFStab= 0
UNET SFStab= 0
UNET WFX= 1
UNET SFX= 1
UNET Gravity=32.17405
UNET 1D Methodology=Finite Difference
UNET DSS MLevel= 1
UNET Pardiso=0
UNET DZMax Abort= 0
UNET Use Existing IB Tables= 0
UNET Froude Reduction=False
UNET Froude Limit= 0
UNET Froude Power= 0
UNET D1 Cores= 0
UNET WindReference=Eulerian
UNET WindDragFormulation=Hsu (1988)
UNET D2 Coriolis=0
UNET D2 Cores= 0
UNET D2 Theta= 1
UNET D2 Theta Warmup= 1
UNET D2 Z Tol= 0.01
UNET D2 Volume Tol= 0.01
UNET D2 Max Iterations= 20
UNET D2 Equation= 0
UNET D2 RampUpFraction=0.1
UNET D2 TimeSlices= 1
UNET D2 Turbulence Formulation=Non-Conservative (original)
UNET D2 Eddy Viscosity=0.3
UNET D2 Transverse Eddy Viscosity=0.1
UNET D2 Smagorinsky Mixing=0
UNET D2 BCVolumeCheck=0
UNET D2 Cores=0
UNET D2 SolverType=PARDISO (Direct)
UNET D2 Minimum Iterations= 3
UNET D2 Maximum Iterations= 30
UNET D2 Restart Number= 10
UNET D2 Relaxation Coeff=1.3
UNET D2 SOR Precondition Iterations= 10
UNET D2 ILUT Maximum Fill= 8
UNET D2 ILUT Tolerance=1E-08
UNET D2 Convergence Tolerance=0.00001
UNET D1D2 MaxIter= 0
UNET D1D2 ZTol=0.01
UNET D1D2 QTol=0.1
UNET D1D2 MinQTol=1
Write IC File= 0
Write IC File at Fixed DateTime=0
Write IC File at Sim End=0
Echo Input=False
Echo Parameters=False
Echo Output=False
Write Detailed= 0
HDF Write Warmup=0
HDF Write Time Slices=0
HDF Flush=0
HDF Compression= 1
HDF Chunk Size= 1
HDF Spatial Parts= 1
HDF Use Max Rows=0
HDF Fixed Rows= 1
Calibration Method= 0
Calibration Iterations= 20
Calibration Max Change=0.05
Calibration Tolerance=0.2
Calibration Maximum=1.5
Calibration Minimum=0.5
Calibration Optimization Method= 1
WQ AD Non Conservative
WQ ULTIMATE=-1
WQ Max Comp Step=1HOUR
WQ Output Interval=15MIN
WQ Output Selected Increments= 0
WQ Output face flow=0
WQ Output face velocity=0
WQ Output face area=0
WQ Output face dispersion=0
WQ Output cell volume=0
WQ Output cell surface area=0
WQ Output cell continuity=0
WQ Output cumulative cell continuity=0
WQ Output face conc=0
WQ Output face dconc_dx=0
WQ Output face courant=0
WQ Output face peclet=0
WQ Output face adv mass=0
WQ Output face disp mass=0
WQ Output cell mass=0
WQ Output cell source sink temp=0
WQ Output nsm pathways=0
WQ Output nsm derived pathways=0
WQ Create Restart=0
WQ Fixed Restart=0
WQ System Summary=0
WQ Write To DSS=0
Sorting and Armoring Iterations= 10
XS Update Threshold= 0.02
Bed Roughness Predictor= 0
Hydraulics Update Threshold= 0.02
Energy Slope Method= 1
Volume Change Method= 1
Sediment Retention Method= 0
Sediment TS Multiplier= 1
Warm Up Method= 0
XS Weighting Method= 0
Number of US Weighted Cross Sections= 1
Number of DS Weighted Cross Sections= 1
Upstream XS Weight=0
Main XS Weight=1
Downstream XS Weight=0
Number of DS XS's Weighted with US Boundary= 1
Upstream Boundary Weight= 1
Weight of XSs Associated with US Boundary= 0
Number of US XS's Weighted with DS Boundary= 1
Downstream Boundary Weight= 0.5
Weight of XSs Associated with DS Boundary= 0.5
Percentile Method= 0
Sediment Output Level= 3
Mass or Volume Output= 0
Output Increment Type= 1
Profile and TS Output Increment= 1
Transport Output Increment 1
XS Output Flag= 0
XS Output Increment= 10
Read HDF5 Sediment Hotstart= 0
Sediment Hotstart Type= 0
Write Gradation File= 0
Read Gradation Hotstart= 0
Write HDF5 File= 1
Write Binary Output= 1
Write DSS Sediment File= 0
DSS Sediment Output Type= 1
SV Curve= 0
Specific Gage Flag= 0
Subcell Erosion Methods= 0
Subcell Deposition Methods= 0
Advection Scheme= 1
Matrix Solver= 0
Implicit Weighting Factor= 1
Maximum Outer Loop Convergence Iterations= 5
Convergence Maximum Absolute= 0.001
Convergence RMSE= 0.0001
Grain Fractions Max Abs Error= 0.001
Max Subgrid Regions= 1
Max Subgrid Length Scale= 3.402823E+38
Initial Layer Thickness= 3.402823E+38
Min Layer Thickness= 3.402823E+38
Max Layer Thickness= 3.402823E+38
Number of Layers= 5

--- BRUSHYFKT1.f01 (steady flow) ---

Flow Title=Flows
Program Version=6.31
Number of Profiles= 1
Profile Names=01pct
River Rch & RM=BRUSHYFKT1,Main            ,2790
     245
River Rch & RM=BRUSHYFKT1,Main            ,2302
     285
Boundary for River Rch & Prof#=BRUSHYFKT1,Main            , 1
Up Type= 0
Dn Type= 3
Dn Slope=0.00331
DSS Import GetInterval= 0
DSS Import GetPeak= 0
DSS Import FillOption= 0

--- BRUSHYFKT1.g01 (geometry) ---

Geom Title=Geometry
Program Version=6.31

River Reach=BRUSHYFKT1      ,Main
Reach XY= 30
2178838.01559504724115.0941073162178768.83365859724162.617985903
2178735.45406354 724238.30974368 2178623.6772567 724374.44201328
2178590.14223975724446.0263763852178563.70116869724465.373501548
2178548.86837273724496.973805982 2178549.5132769724533.733343793
 2178466.3206387 724639.497628022178401.49202487724843.170821911
2178359.12182076 724940.099918982178343.93183686725157.337364307
2178310.84825283725173.5889494452178300.98121899725242.077772524
2178271.96053125725281.5459078572178225.52743086725318.111974416
2178164.58398659725417.3627265052178137.30454011725434.775139152
2178095.16992504725518.2085268262178104.90378306725595.962756914
2178075.28526915725617.5889734222178082.33729627725656.140055023
2178068.23324203725691.4001906332178062.12148519 725795.77019204
2177965.92340336726051.282686462 2177952.1623023726099.446540194
2177955.11110967726142.6957149752178011.42567756726282.044049496
2178033.48140025726363.882388938 2178205.2442083726509.460017034

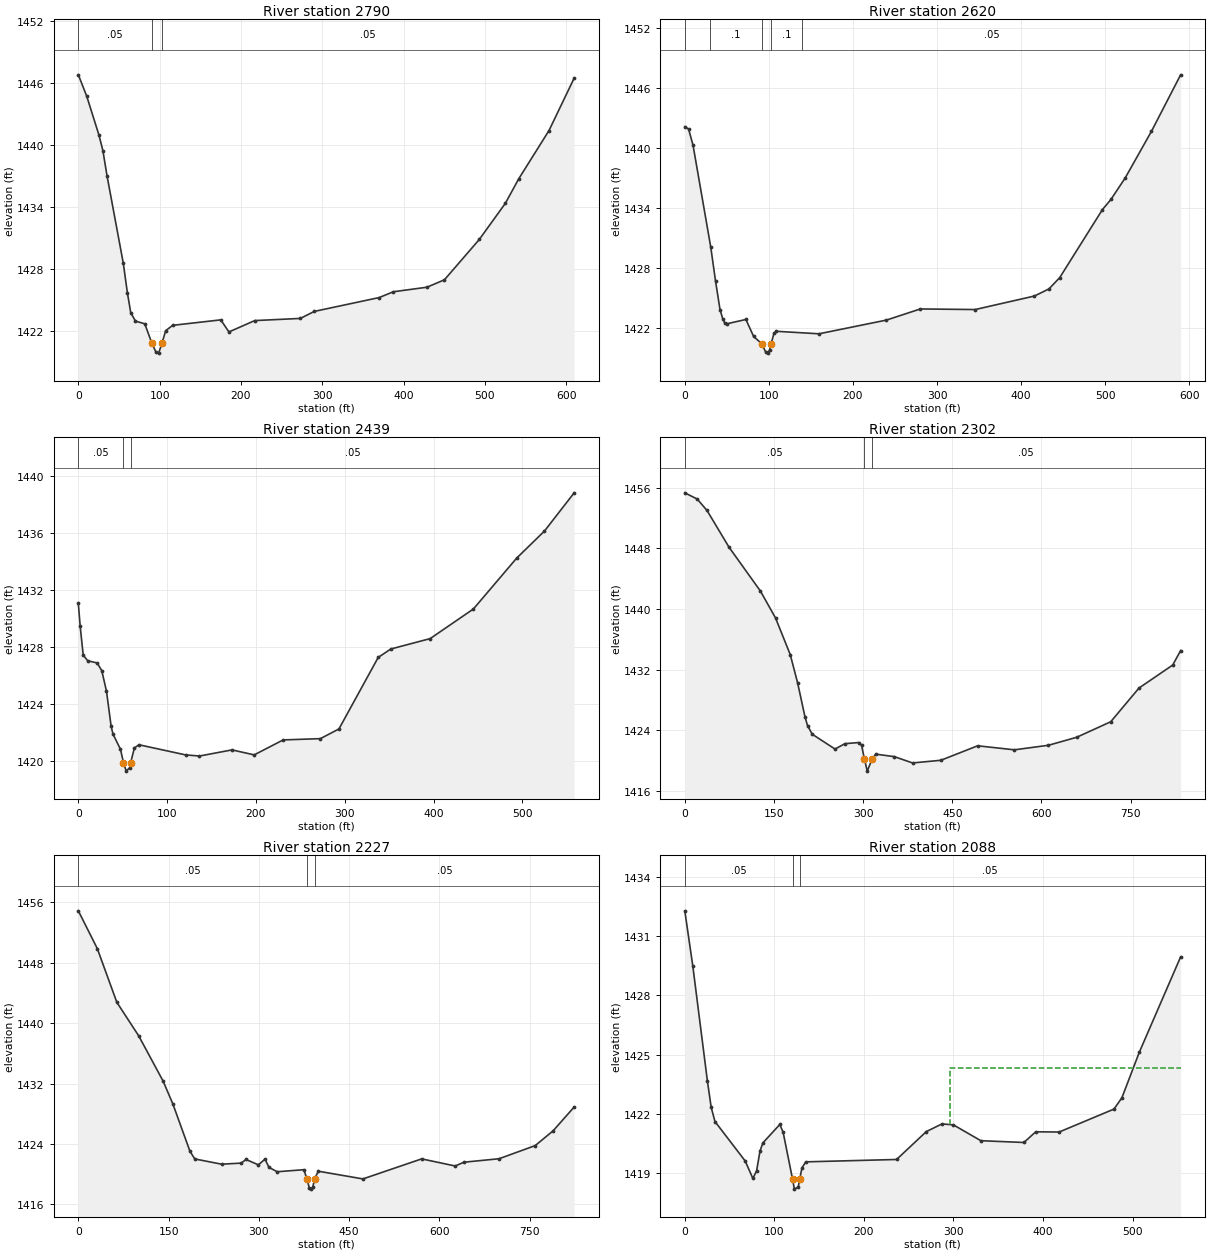
Type RM Length L Ch R = 1 ,2790    ,170,170,170
XS GIS Cut Line= 2
2178774.05049651724040.9526271412179139.66400043724529.020414675
#Sta/Elev= 30
       0 1446.81    10.3 1444.75    25.3 1440.99    30.2 1439.48    35.3 1437.03
    55.3 1428.57    60.3 1425.73    64.5 1423.77    70.3 1422.97    81.7 1422.71
    90.2 1420.88    95.2 1420.01    98.8 1419.87  102.96 1420.86   107.4 1422.04
     116 1422.56   175.2 1423.09   185.2 1421.92     217 1423.02   273.1 1423.23
   290.3 1423.91   370.1 1425.25   387.4 1425.81   428.8 1426.25   450.3 1426.97
   493.1 1430.87   525.1 1434.36   541.7 1436.75   578.9 1441.42609.8224 1446.49
#Mann= 3 ,0,0
       0     .05       0    90.2    .045       0  102.96     .05       0
Bank Sta=90.2,102.96
XS Rating Curve= 0 ,0
Exp/Cntr(USF)=0,0
Exp/Cntr=0.3,0.1

Type RM Length L Ch R = 1 ,2620    ,181.1,181.6,181
XS GIS Cut Line= 2
2178656.84425362724180.9003798392179097.67967462724572.754087393
#Sta/Elev= 30
       0 1442.14     4.5 1441.91     9.8 1440.29    30.9 1430.11    36.6 1426.71
    41.9 1423.88    45.1 1422.98    47.3 1422.57    50.7 1422.48    72.7  1422.9
    81.9  1421.2    91.51420.478    96.1 1419.67    98.9 1419.54   100.8 1419.85
  102.68 1420.46   106.1 1421.54   108.8 1421.72   159.7 1421.47   239.9 1422.84
   280.2 1423.95   345.4 1423.89   415.9 1425.24   433.2 1425.95     446 1427.08
   496.8 1433.87   506.9 1434.88   523.9 1437.03   555.1 1441.68   589.8 1447.32
#Mann= 5 ,-1,0
       0     .05       0      30      .1       0    91.5    .045       0
  102.68      .1       0     140     .05       0
Bank Sta=91.5,102.68
XS Rating Curve= 0 ,0
Exp/Cntr(USF)=0,0
Exp/Cntr=0.3,0.1

Type RM Length L Ch R = 1 ,2439    ,136.8,136.5,134.8
XS GIS Cut Line= 4
2178575.98902112724350.3980943022178825.96632675 724561.48071002
2178968.79016865724629.4771473792179032.72180573724664.408922475
#Sta/Elev= 30
       0 1431.08     2.1 1429.46     5.5 1427.45    10.5 1427.06    21.2  1426.9
    26.4 1426.36    31.7 1424.92    36.9 1422.47      39 1421.91    47.4 1420.85
    50.81419.915    53.9 1419.31    57.8 1419.55    58.9  1419.9    63.1 1420.94
    68.3 1421.16   120.7 1420.45   136.4 1420.37     173  1420.8     198 1420.45
   230.6  1421.5   272.5 1421.59   293.4 1422.27   337.6 1427.29   351.8 1427.88
   396.1 1428.61   444.8 1430.69   493.5 1434.26   524.8 1436.16   558.2 1438.84
#Mann= 3 ,-1,0
       0     .05       0    50.8    .045       0    58.9     .05       0
Bank Sta=50.8,58.9
XS Rating Curve= 0 ,0
Exp/Cntr(USF)=0,0
Exp/Cntr=0.3,0.1

Type RM Length L Ch R = 1 ,2302    ,74.7,75,73.1
XS GIS Cut Line= 3
2178462.66674675724208.8899303792178530.89127619724487.036088865
2178990.96951319724784.425063348
#Sta/Elev= 30
       0 1455.33    20.9 1454.51    37.4    1453    74.4 1448.16   127.2 1442.38
   152.7 1438.82   177.4    1434   189.8 1430.27   202.1 1425.82   206.5 1424.63
   214.5 1423.49   252.8 1421.54   269.4 1422.25   292.7  1422.4   297.4 1422.04
   302.2 1420.23     307 1418.63   314.9 1420.18   321.3 1420.87   352.5 1420.54
   383.2 1419.71   430.8 1420.06   492.7 1421.97   554.6 1421.44   611.8 1422.04
   659.2 1423.09   716.6 1425.14   764.2 1429.59   820.9 1432.62   834.2 1434.53
#Mann= 3 ,-1,0
       0     .05       0   302.2    .045       0   314.9     .05       0
Bank Sta=302.2,314.9
XS Rating Curve= 0 ,0
Exp/Cntr(USF)=0,0
Exp/Cntr=0.3,0.1

Type RM Length L Ch R = 1 ,2227    ,141.7,139.6,138.2
XS GIS Cut Line= 3
2178153.03234391724557.0099652142178434.67719621724511.526945587
2178898.25412703724786.174410257
#Sta/Elev= 30
       0 1454.84    31.5 1449.85      64 1442.74   100.3 1438.31   140.9 1432.32
   157.2 1429.28   185.5 1423.04   193.6 1422.02   238.2 1421.33   270.6 1421.47
   278.7 1421.95   299.3 1421.24   310.3    1422   316.8 1420.91   330.5 1420.33
   374.9  1420.6     380 1419.34   383.9 1418.21   386.9 1418.03   389.8 1418.34
   392.7  1419.4   398.9  1420.4     473 1419.38   570.6 1422.03   626.4 1421.09
   640.9 1421.59   699.3 1422.05   759.4 1423.79   789.2 1425.75   824.1 1428.89
#Mann= 3 ,-1,0
       0     .05       0     380    .045       0   392.7     .05       0
Bank Sta=380,392.7
XS Rating Curve= 0 ,0
Exp/Cntr(USF)=0,0
Exp/Cntr=0.3,0.1

Type RM Length L Ch R = 1 ,2088    ,196.5,196.2,195.7
XS GIS Cut Line= 4
2178335.42141401724645.8156943822178355.02966756724648.904880472
2178616.11752235724737.4998715522178852.19471495724841.965491296
#Sta/Elev= 30
       0 1432.28     8.9  1429.5    25.3 1423.65    29.5 1422.33    33.7 1421.62
    67.5 1419.62      76 1418.74    80.2 1419.13      84 1420.13    87.2 1420.54
   106.1 1421.47   109.8 1421.08   120.3 1418.71   122.4  1418.2   126.7 1418.31
   128.2 1418.69   130.9 1419.28   135.1 1419.58   236.5  1419.7   269.7 1421.11
   287.2  1421.5     300 1421.45   330.6 1420.65   378.7 1420.56   391.9  1421.1
   418.1 1421.09   479.3 1422.25   488.1 1422.82   507.6 1425.13   553.7 1429.95
#Mann= 3 ,-1,0
       0     .05       0   120.3    .045       0   128.2     .05       0
#XS Ineff= 2 , 0
                          295.77         1424.34
Permanent Ineff=
       F       F
Bank Sta=120.3,128.2
XS Rating Curve= 0 ,0
Exp/Cntr(USF)=0,0
Exp/Cntr=0.3,0.1

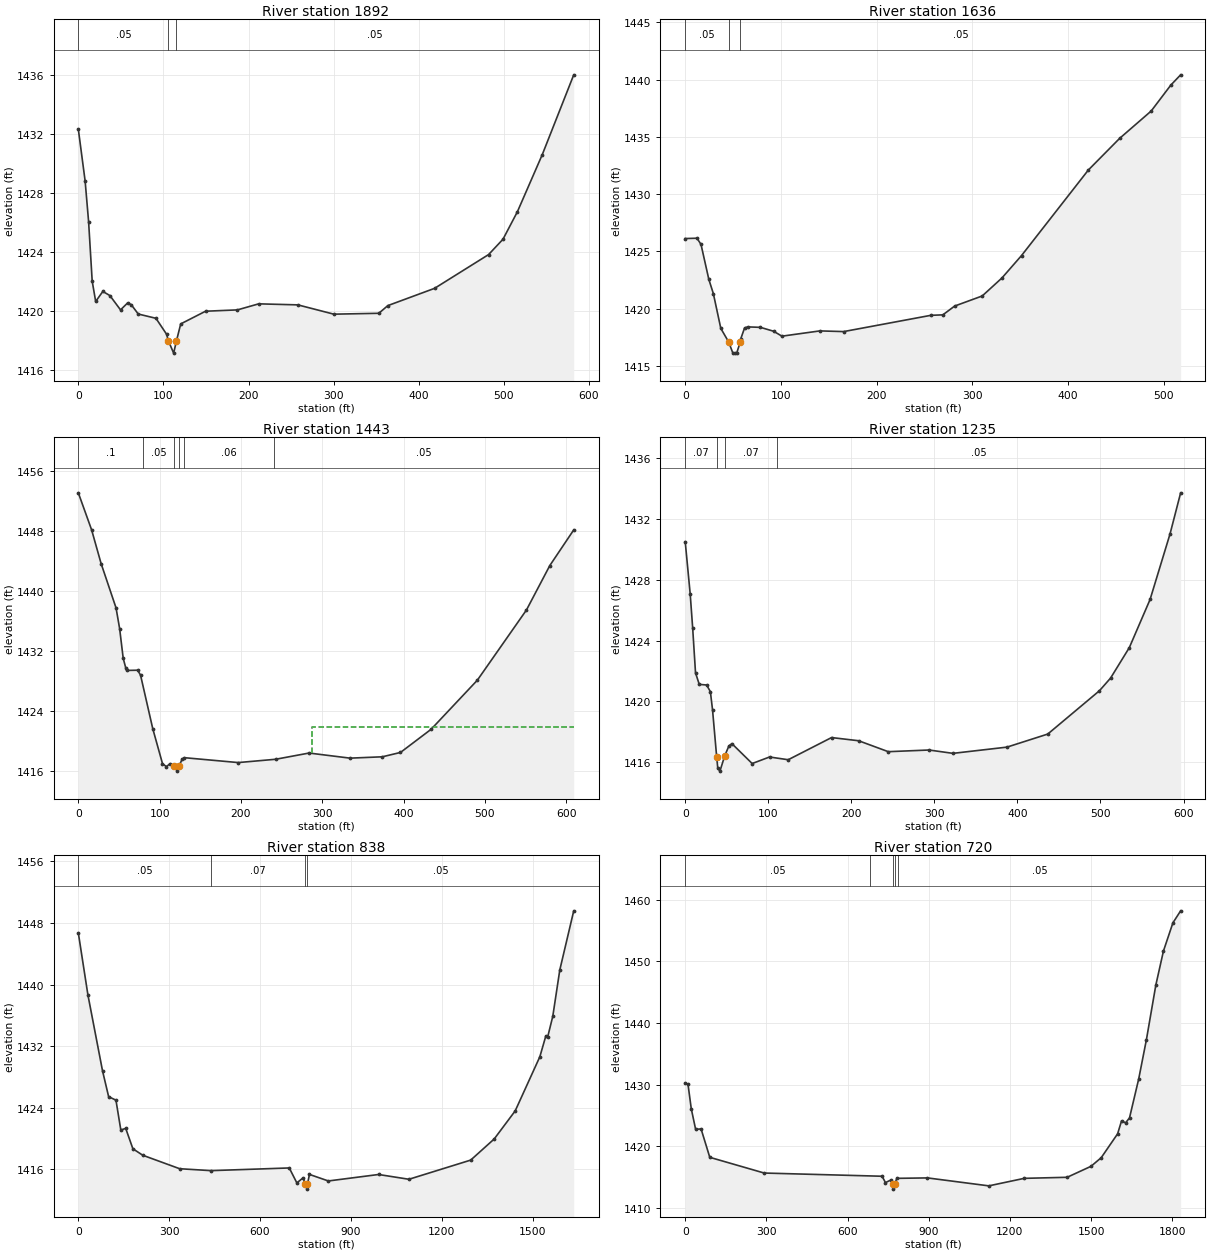
Type RM Length L Ch R = 1 ,1892    ,255.5,255.6,255.5
XS GIS Cut Line= 3
2178284.52439344724836.5236194742178519.96912674724904.166863698
2178838.77433704725013.407748773
#Sta/Elev= 30
       0 1432.34       8 1428.83    12.1 1426.06    16.3 1422.04    20.4 1420.66
    28.8 1421.34    37.1 1421.06    49.6 1420.09    57.9 1420.56    62.1 1420.45
    70.4 1419.81    91.2 1419.52   103.7 1418.44   105.81417.994     112 1417.16
   115.3 1417.99   120.3 1419.14   149.5    1420   186.9 1420.09   211.9  1420.5
   257.9 1420.43   300.2  1419.8     353 1419.86   363.6 1420.38   418.5 1421.55
     482 1423.84   498.9 1424.88   515.8 1426.74   545.1 1430.62     582 1436.02
#Mann= 3 ,-1,0
       0     .05       0   105.8    .045       0   115.3     .05       0
Bank Sta=105.8,115.3
XS Rating Curve= 0 ,0
Exp/Cntr(USF)=0,0
Exp/Cntr=0.3,0.1

Type RM Length L Ch R = 1 ,1636    ,179.5,193.1,192
XS GIS Cut Line= 3
2178292.28746931725101.028577182 2178573.7558388725177.266756563
2178794.20419549725228.464835625
#Sta/Elev= 30
       0 1426.12    12.3 1426.15    16.5 1425.61    24.7 1422.55    29.4 1421.32
    37.2 1418.28    45.5 1417.08    49.6 1416.17    52.2 1416.12    53.8 1416.12
   57.47 1417.07    57.9 1417.33      62 1418.31    65.2 1418.41    78.6 1418.37
    92.4 1418.03   101.1  1417.6   140.8 1418.06   165.6    1418   256.8 1419.42
   269.3 1419.46   281.7 1420.23   310.5 1421.11   331.1 1422.68   351.6 1424.64
   421.4  1432.1   454.2 1434.87   487.1 1437.25   507.6 1439.51   517.9 1440.41
#Mann= 3 ,-1,0
       0     .05       0    45.5    .045       0   57.47     .05       0
Bank Sta=45.5,57.47
XS Rating Curve= 0 ,0
Exp/Cntr(USF)=0,0
Exp/Cntr=0.3,0.1

Type RM Length L Ch R = 1 ,1443    ,208.1,207.7,206.6
XS GIS Cut Line= 3
2178170.28786622725225.1931638742178610.05690748 725433.80155524
2178728.45626474725464.810910714
#Sta/Elev= 30
       0 1453.08    16.4 1448.13      28 1443.66    46.4 1437.74    50.8 1434.98
    55.2 1431.02    58.5 1429.68    59.6 1429.41    72.9 1429.44    76.5 1428.79
    91.5 1421.66   103.5 1416.99   108.3 1416.59   112.8 1416.99   117.2 1416.73
   121.5 1415.99   124.11416.723   127.5 1417.55   130.5 1417.78   196.6 1417.13
   242.6 1417.57   283.7  1418.4   334.1 1417.72   373.8  1417.9   396.1 1418.48
   433.8 1421.57   490.6 1428.11     551 1437.47   579.7 1443.39   609.1 1448.14
#Mann= 6 ,-1,0
       0      .1       0      80     .05       0   117.2    .045       0
   124.1     .05       0     130     .06       0     240     .05       0
#XS Ineff= 2 , 0
                           287.1          1421.9
Permanent Ineff=
       F       F
Bank Sta=117.2,124.1
XS Rating Curve= 0 ,0
Exp/Cntr(USF)=0,0
Exp/Cntr=0.3,0.1

Type RM Length L Ch R = 1 ,1235    ,395.7,396.5,393.4
XS GIS Cut Line= 3
2178105.05549314725408.2427579782178541.31145624725624.355281409
2178648.65718153 725602.22644156
#Sta/Elev= 30
       0 1430.51       6 1427.07       9 1424.81    12.4 1421.88    16.9 1421.12
    25.8 1421.08    30.3 1420.64    32.9 1419.44    37.91416.331    39.2 1415.61
    41.8 1415.41    47.51416.407    52.6 1417.07    56.2 1417.22    80.6 1415.91
   101.5 1416.34     124 1416.16   176.2 1417.62   208.8 1417.41   244.5 1416.69
   293.6  1416.8   322.4 1416.58   387.4 1416.99   436.5 1417.85   498.7  1420.7
   512.2 1421.54   534.7 1423.54   559.7 1426.71   583.7 1431.02   596.5 1433.73
#Mann= 4 ,-1,0
       0     .07       0    37.9    .045       0    47.5     .07       0
     110     .05       0
Bank Sta=37.9,47.5
XS Rating Curve= 0 ,0
Exp/Cntr(USF)=0,0
Exp/Cntr=0.3,0.1

Type RM Length L Ch R = 1 ,838     ,118.1,118.5,118.6
XS GIS Cut Line= 4
2177613.19631275725349.6203589272177647.85796465725669.574068799
2178589.05512786725938.8684412742178890.34487132725792.222990916
#Sta/Elev= 30
       0 1446.72    31.7 1438.66      80 1428.79   100.1 1425.45   124.3 1424.99
   140.4 1421.11   156.5 1421.33   180.2 1418.68   212.8 1417.84   334.7 1416.09
   438.2 1415.84   696.6 1416.19   721.6 1414.25   742.4 1414.91  749.58 1414.05
   754.8 1413.44   756.6 1414.07   763.2 1415.35   825.6  1414.5   991.4 1415.34
  1091.7 1414.72  1295.7 1417.21  1373.2 1419.95  1442.6  1423.6    1524 1430.63
  1543.8 1433.34  1549.8 1433.19  1566.7 1435.88  1589.9 1441.91  1635.9 1449.58
#Mann= 4 ,-1,0
       0     .05       0   438.2     .07       0  749.58    .045       0
   756.6     .05       0
Bank Sta=749.58,756.6
XS Rating Curve= 0 ,0
Exp/Cntr(USF)=0,0
Exp/Cntr=0.3,0.1

Type RM Length L Ch R = 1 ,720     ,,,
XS GIS Cut Line= 4
 2177558.7721867725442.918860726 2177593.4338386725762.872570598
2178767.87725631726135.1840388092178995.30568584725976.876275726
#Sta/Elev= 30
       0 1430.22    10.3 1430.07    22.4 1426.09    38.5 1422.76    58.6 1422.83
    90.8 1418.22     292 1415.67   727.5 1415.15   740.1 1414.12   761.1 1414.56
   766.3 1413.85   769.5 1413.06   773.7 1413.82   782.1 1414.81   895.4 1414.88
    1122 1413.59    1253 1414.81  1411.5 1414.98  1499.6 1416.76  1537.4 1418.16
  1598.1 1422.04  1612.7 1424.15  1627.4 1423.81    1642 1424.62  1676.1 1430.96
  1704.4 1437.29  1739.4 1446.19  1767.4 1451.69  1802.4 1456.27    1831 1458.22
#Mann= 5 ,-1,0
       0     .05       0   684.2     .07       0   766.3    .045       0
   773.7     .07       0   787.6     .05       0
Bank Sta=766.3,773.7
XS Rating Curve= 0 ,0
Exp/Cntr(USF)=0,0
Exp/Cntr=0.3,0.1
LCMann Table=0

Chan Stop Cuts=-1
Use User Specified Reach Order=0
Composite Channel Slope=5